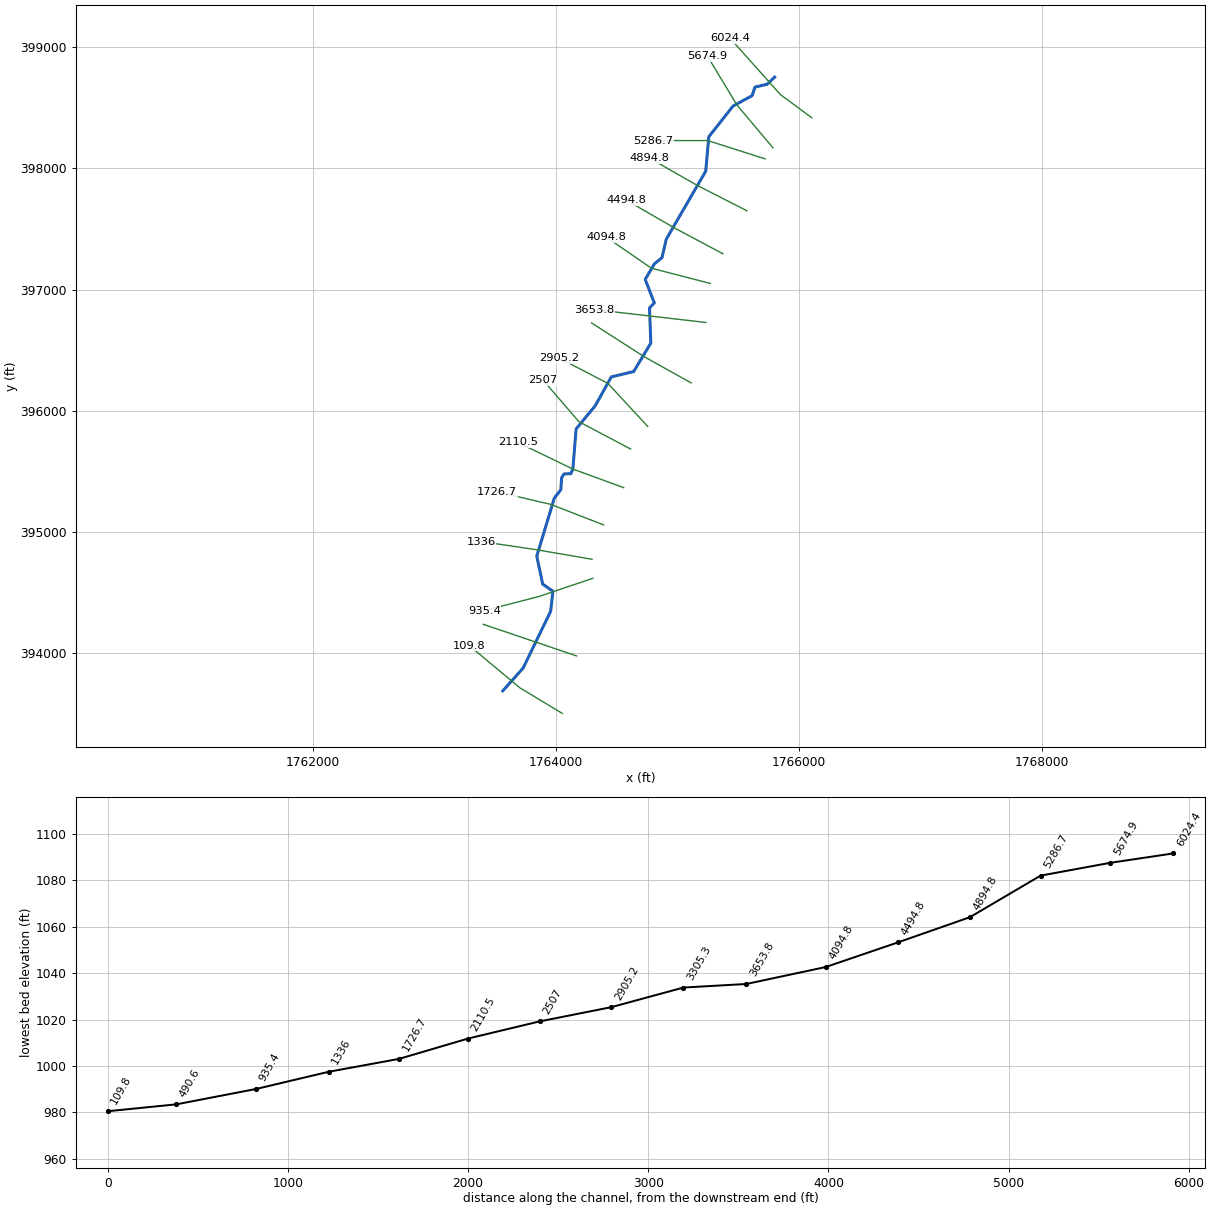
--- LrlRn1.prj (project) ---

Proj Title=LrlRn1
Current Plan=p01
Default Exp/Contr=0,0
English Units
Geom File=g01
Flow File=f01
Plan File=p01
BEGIN DESCRIPTION:
END DESCRIPTION:
DSS Export Rating Curves= 0
DSS Export Rating Curve Sorted= 0
DSS Export Volume Flow Curves= 0
DXF OffsetX= 0
DXF OffsetY= 0
DXF ScaleX= 0
DXF ScaleY= 0

--- LrlRn1.p01 (plan) ---

Plan Title=Floodplain
Program Version=4.00
Geom File=g01
Flow File=f01
K Sum by GR=0
Std Step Tol=0.01
Critical Tol=0.01
Num of Std Step Trials=20
Max Error Tol=0.3
Flow Tol Ratio=0.001
Split Flow NTrial=30
Split Flow Tol=0.02
Split Flow Ratio=0.02
Log Output Level=0
Friction Slope Method=1
Unsteady Friction Slope Method=2
Unsteady Bridges Friction Slope Method=1
Global Log Level=0
CheckData=False
Run HTab=0
Run UNet=0
Run PostProcess=0
UNET Theta=0
UNET Theta Warmup=0
UNET ZTol=0
UNET ZSATol=0
UNET MxIter=0
UNET MaxInSteps=0
UNET DtIC=0
UNET DtMin=0
UNET MaxCRTS=0
UNET WFStab=0
UNET SFStab=0
UNET WFX=0
UNET SFX=0
UNET DSS MLevel=0
UNET DZMax Abort=0
UNET Convert EG Bridges=0
UNET Use Existing IB Tables=0
UNET Froude Limit=0
UNET Froude Power=0
Write IC File=0
Echo Input=False
Echo Output=False
Write Detailed=0

--- LrlRn1.f01 (steady flow) ---

Flow Title=NFF Regression Equation
Program Version=4.00
Number of Profiles= 1
Profile Names=P100yr
River Rch & RM=LrlRn1,Main            ,6024.4
  730.54
River Rch & RM=LrlRn1,Main            ,4894.8
784.4978
River Rch & RM=LrlRn1,Main            ,3305.3
859.0876
River Rch & RM=LrlRn1,Main            ,109.8
 943.847
Boundary for River Rch & Prof#=LrlRn1,Main            , 1
Up Type= 0
Dn Type= 3
Dn Slope=0.017845
DSS Import GetInterval= 0
DSS Import GetPeak= 0
DSS Import FillOption= 0

--- LrlRn1.g01 (geometry) ---

Geom Title=USGS 3m DEM
Program Version=4.00

River Reach=LrlRn1     ,Main
Reach XY= 30
     1765803.160      398752.756     1765741.342      398693.882
     1765641.255      398670.332     1765617.705      398599.682
     1765460.646      398514.194     1765261.364      398260.749
     1765235.815      397976.646     1764911.211      397416.304
     1764875.886      397263.230     1764814.067      397213.186
     1764737.530      397083.663     1764812.726      396890.308
     1764772.855      396848.164     1764784.112      396559.195
     1764643.331      396324.181     1764458.337      396279.544
     1764327.689      396043.981     1764168.895      395849.958
     1764142.382      395522.844     1764125.982      395481.332
     1764069.597      395479.223     1764049.326      395447.308
     1764043.195      395349.201     1763989.031      395278.686
     1763844.935      394800.411     1763893.989      394570.471
     1763977.790      394511.198     1763959.394      394346.663
     1763732.755      393877.657     1763565.192      393689.557

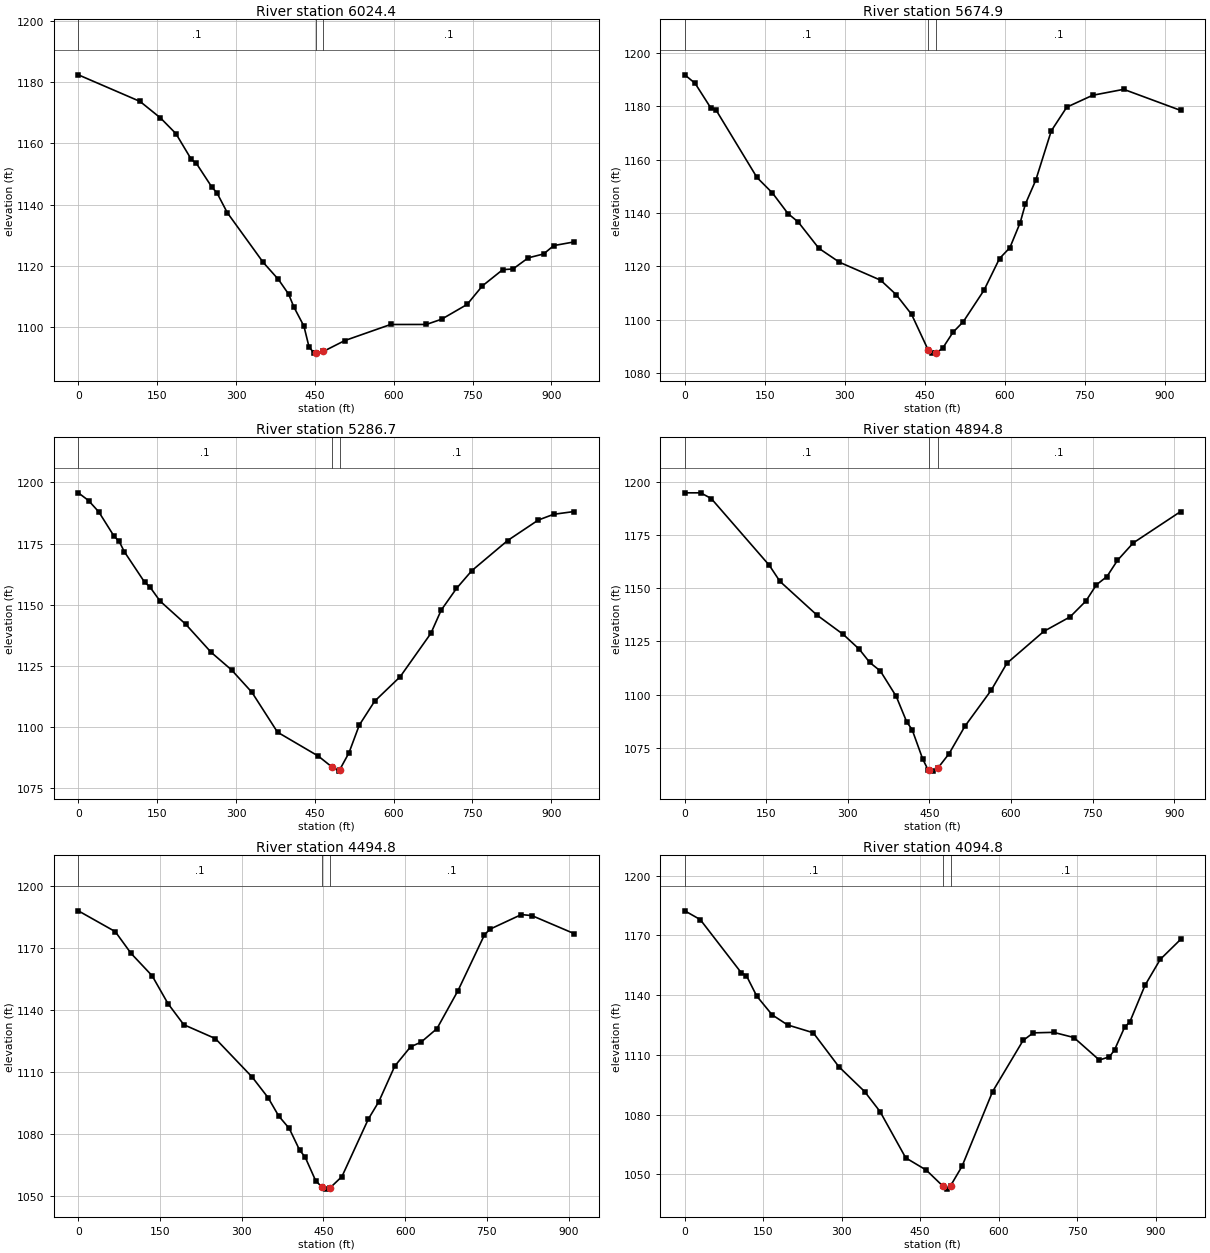
Type RM Length L Ch R = 1 ,6024.4,348.563,349.467,346.24
XS GIS Cut Line= 3
     1766109.062      398417.060     1765850.099      398609.179
     1765436.953      399072.651
#Sta/Elev= 30
       0 1182.34   117.3 1173.66   156.3 1168.26   185.7 1163.13   215.0 1154.71
   224.7 1153.39   254.0 1145.69   263.8 1143.78   283.4 1137.33   351.6 1121.13
   380.7 1115.53   400.1 1110.73   409.8 1106.63   429.2 1100.28   438.9 1093.50
   448.6 1091.48   451.4 1091.52   466.4 1092.06   506.8 1095.57   594.1 1100.83
   662.0 1100.84   691.1 1102.55   739.6 1107.37   768.7 1113.43   807.5 1118.74
   826.9 1118.95   856.0 1122.59   885.1 1123.85   904.5 1126.59   943.3 1127.79
#Mann= 3 , 0 , 0
       0     0.1       0   451.4   0.045       0   466.4     0.1       0
Bank Sta=   451.4,   466.4
Exp/Cntr=0.3,0.1

Type RM Length L Ch R = 1 ,5674.9,374.926,388.22,410.311
XS GIS Cut Line= 3
     1765789.368      398169.436     1765491.218      398524.794
     1765251.519      398924.030
#Sta/Elev= 30
       0 1191.82    19.3 1188.63    48.3 1179.53    58.0 1178.81   135.3 1153.32
   164.3 1147.51   193.3 1139.81   212.6 1136.63   251.3 1126.76   289.9 1121.54
   367.2 1114.79   396.2 1109.40   425.2 1101.97   456.4 1088.56   463.9 1087.45
   471.4 1087.55   483.3 1089.27   502.7 1095.25   522.1 1099.24   560.9 1111.04
   590.0 1122.93   609.4 1126.99   628.8 1136.43   638.5 1143.37   657.9 1152.29
   687.0 1170.80   716.1 1179.70   764.6 1184.15   822.8 1186.38   929.5 1178.48
#Mann= 3 , 0 , 0
       0     0.1       0   456.4   0.045       0   471.4     0.1       0
Bank Sta=   456.4,   471.4
Exp/Cntr=0.3,0.1

Type RM Length L Ch R = 1 ,5286.7,395.611,391.862,381.877
XS GIS Cut Line= 3
     1765724.817      398078.402     1765252.683      398229.322
     1764804.860      398229.322
#Sta/Elev= 30
       0 1195.77    19.4 1192.62    38.9 1187.98    68.0 1178.01    77.8 1175.86
    87.5 1171.69   126.3 1159.15   136.1 1157.29   155.5 1151.49   204.1 1142.06
   252.7 1130.52   291.6 1123.31   330.4 1114.13   379.0 1097.85   456.8 1088.04
   482.1 1083.69   495.7 1081.91   497.1 1082.36   515.1 1089.45   534.6 1100.73
   563.8 1110.50   612.5 1120.55   670.9 1138.30   690.4 1147.75   719.6 1156.66
   748.8 1163.93   816.9 1176.25   875.3 1184.64   904.6 1186.99   943.5 1188.12
#Mann= 3 , 0 , 0
       0     0.1       0   482.1   0.045       0   497.1     0.1       0
Bank Sta=   482.1,   497.1
Exp/Cntr=0.3,0.1

Type RM Length L Ch R = 1 ,4894.8,400.364,399.987,399.87
XS GIS Cut Line= 3
     1765573.900      397650.724     1765167.107      397858.770
     1764772.255      398084.914
#Sta/Elev= 30
       0 1194.69    29.2 1194.69    48.6 1192.02   155.5 1160.63   175.0 1153.11
   243.0 1137.30   291.6 1128.18   320.8 1121.28   340.2 1115.03   359.7 1111.04
   388.9 1099.10   408.3 1087.05   418.0 1083.57   437.5 1069.74   447.2 1064.75
     450 1064.54   456.9 1064.03     465 1065.31   486.0 1072.21   515.0 1085.04
   563.4 1101.97   592.4 1114.68   660.2 1129.63   708.6 1136.45   737.7 1143.89
   757.0 1151.51   776.4 1155.39   795.8 1163.00   824.8 1171.18   911.9 1185.90
#Mann= 3 , 0 , 0
       0     0.1       0     450   0.045       0     465     0.1       0
Bank Sta=     450,     465
Exp/Cntr=0.3,0.1

Type RM Length L Ch R = 1 ,4494.8,395.644,400,396.486
XS GIS Cut Line= 3
     1765377.798      397295.336     1764976.379      397509.426
     1764582.290      397737.509
#Sta/Elev= 30
       0 1187.81    67.8 1177.75    96.8 1167.22   135.5 1156.39   164.6 1142.92
   193.6 1132.72   251.7 1125.99   319.4 1107.31   348.5 1097.38   367.8 1088.58
   387.2 1082.54   406.5 1071.91   416.2 1068.79   435.6 1057.31   447.4 1054.09
   454.9 1053.17   462.4 1053.84   484.0 1059.27   532.4 1087.05   551.8 1095.55
   580.9 1112.67   609.9 1122.00   629.3 1124.29   658.4 1130.82   697.1 1149.24
   745.6 1176.17   755.3 1178.87   813.4 1186.00   832.8 1185.49   910.3 1176.78
#Mann= 3 , 0 , 0
       0     0.1       0   447.4   0.045       0   462.4     0.1       0
Bank Sta=   447.4,   462.4
Exp/Cntr=0.3,0.1

Type RM Length L Ch R = 1 ,4094.8,437.344,441.048,452.967
XS GIS Cut Line= 3
     1765273.499      397050.712     1764788.681      397176.376
     1764420.778      397430.101
#Sta/Elev= 30
       0 1182.35    29.5 1177.96   108.0 1151.24   117.8 1149.78   137.5 1139.55
   166.9 1130.13   196.4 1125.06   245.5 1121.12   294.6 1104.03   343.7 1091.60
   373.2 1081.55   422.3 1058.30   461.6 1052.14   493.3 1044.12   500.8 1042.59
   508.3 1044.40   530.0 1054.09   588.3 1091.55   646.6 1117.23   666.0 1121.06
   704.9 1121.33   743.7 1118.73   792.3 1107.43   811.7 1109.03   821.4 1112.47
   840.9 1124.01   850.6 1126.50   879.7 1144.93   908.9 1157.98   947.8 1168.00
#Mann= 3 , 0 , 0
       0     0.1       0   493.3   0.045       0   508.3     0.1       0
Bank Sta=   493.3,   508.3
Exp/Cntr=0.3,0.1

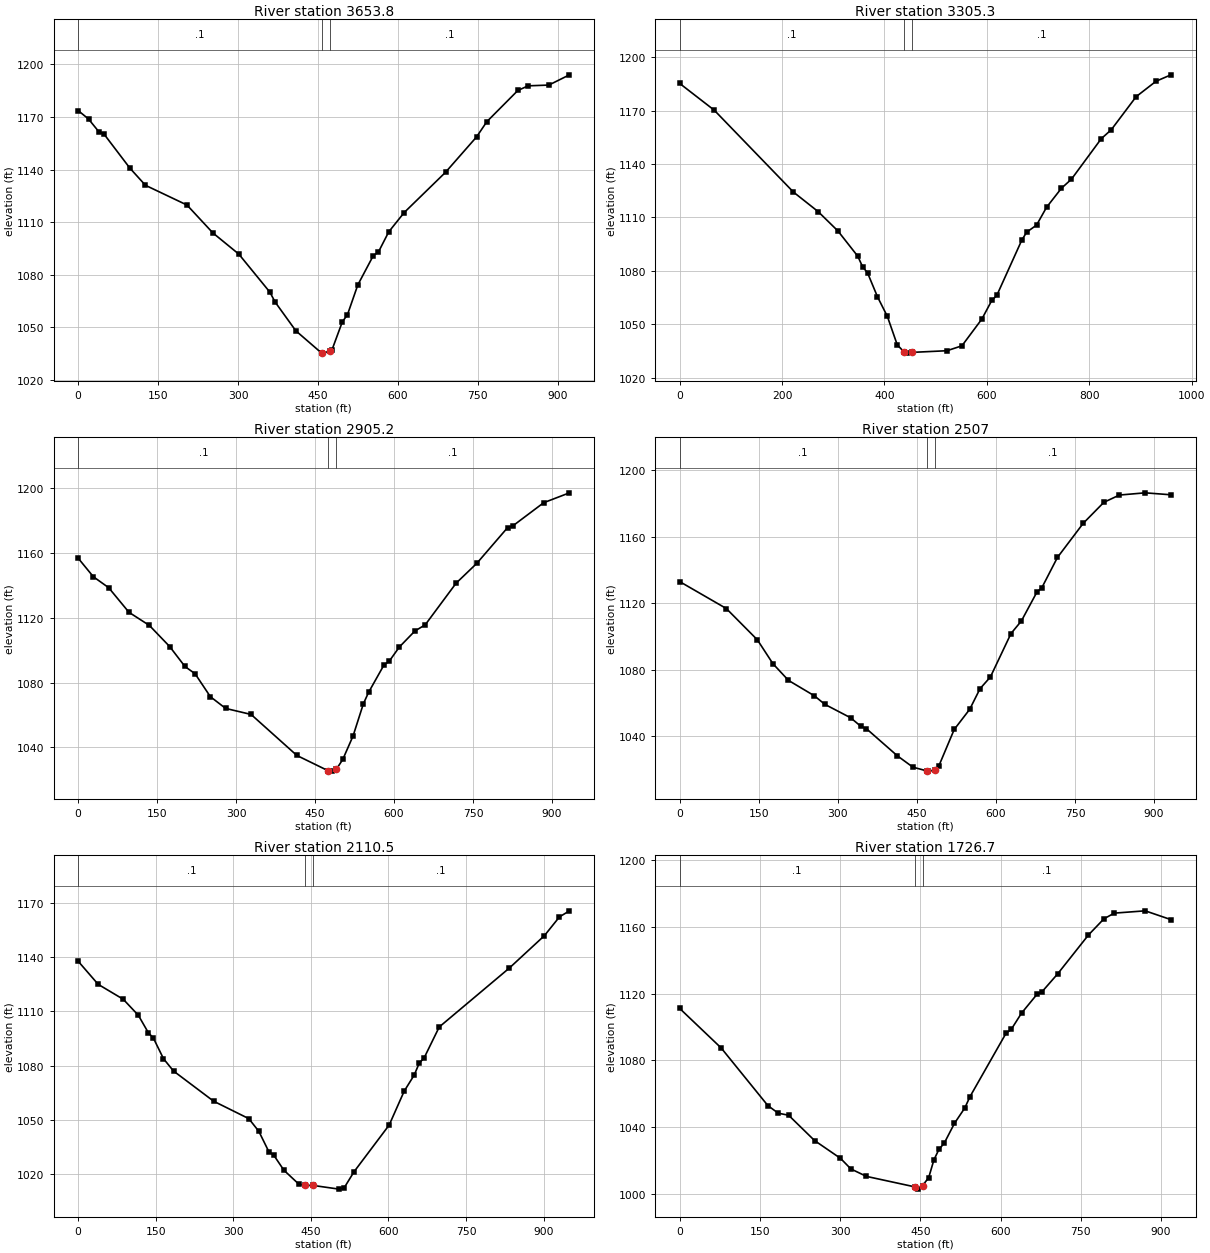
Type RM Length L Ch R = 1 ,3653.8,357.655,348.513,338.025
XS GIS Cut Line= 3
     1765237.384      396728.616     1764831.575      396775.650
     1764321.582      396834.622
#Sta/Elev= 30
       0 1173.73    19.5 1168.89    38.9 1161.62    48.6 1160.28    97.3 1140.79
   126.4 1131.05   204.3 1119.79   252.9 1103.87   301.5 1091.80   359.9 1070.05
   369.6 1064.46   408.5 1048.04   457.0 1035.29   457.1 1035.29   472.1 1036.34
   476.3 1037.10   495.7 1053.11   505.4 1057.23   524.8 1074.21   553.8 1090.88
   563.5 1093.00   582.9 1104.52   611.9 1115.53   689.4 1138.48   747.6 1158.66
   766.9 1167.36   825.1 1185.17   844.4 1187.81   883.2 1188.24   921.9 1194.09
#Mann= 3 , 0 , 0
       0     0.1       0   457.1   0.045       0   472.1     0.1       0
Bank Sta=   457.1,   472.1
Exp/Cntr=0.3,0.1

Type RM Length L Ch R = 1 ,3305.3,406.88,400.103,402.743
XS GIS Cut Line= 3
     1765117.210      396229.675     1764729.191      396446.244
     1764295.889      396725.067
#Sta/Elev= 30
       0 1185.22    67.6 1170.18   222.2 1124.21   270.5 1113.23   309.1 1102.38
   347.8 1088.22   357.4 1082.23   367.1 1078.76   386.4 1065.39   405.7 1054.38
   425.0 1038.41   438.1 1034.48   444.4 1033.76   453.1 1034.17   522.1 1035.11
   551.3 1037.87   590.2 1052.87   609.6 1063.32   619.4 1066.15   668.0 1097.07
   677.7 1101.67   697.1 1105.66   716.6 1115.65   745.7 1126.36   765.2 1131.43
   823.5 1154.19   843.0 1159.20   891.6 1177.78   930.5 1186.45   959.6 1190.04
#Mann= 3 , 0 , 0
       0     0.1       0   438.1   0.045       0   453.1     0.1       0
Bank Sta=   438.1,   453.1
Exp/Cntr=0.3,0.1

Type RM Length L Ch R = 1 ,2905.2,390.052,398.179,391.625
XS GIS Cut Line= 3
     1764758.323      395871.317     1764430.476      396226.069
     1764031.350      396434.020
#Sta/Elev= 30
       0 1156.90    29.0 1145.39    58.0 1138.65    96.6 1123.43   135.3 1115.34
   173.9 1102.28   202.9 1089.96   222.2 1085.46   251.2 1071.30   280.2 1064.06
   328.5 1060.34   415.4 1035.02   475.5 1025.47   483.0 1025.33   490.5 1026.50
   502.6 1032.53   522.2 1047.08   541.7 1066.89   551.5 1073.90   580.9 1090.91
   590.7 1093.17   610.2 1102.04   639.6 1111.89   659.2 1115.70   717.9 1141.44
   757.0 1153.62   815.7 1175.77   825.5 1176.79   884.2 1191.13   933.1 1197.23
#Mann= 3 , 0 , 0
       0     0.1       0   475.5   0.045       0   490.5     0.1       0
Bank Sta=   475.5,   490.5
Exp/Cntr=0.3,0.1

Type RM Length L Ch R = 1 ,2507,393.597,396.467,403.457
XS GIS Cut Line= 3
     1764617.910      395684.813     1764192.075      395910.156
     1763898.255      396251.355
#Sta/Elev= 30
       0 1133.00    88.5 1116.83   147.5 1098.01   177.0 1083.68   206.5 1073.66
   255.6 1064.42   275.3 1059.32   324.5 1051.20   344.1 1046.00   354.0 1044.76
   413.0 1028.39   442.5 1021.57   468.8 1019.34   472.0 1019.19   483.8 1019.80
   491.6 1022.20   520.9 1044.21   550.3 1056.32   569.9 1068.71   589.5 1075.70
   628.6 1101.81   648.2 1109.29   677.6 1126.59   687.3 1129.42   716.7 1147.49
   765.7 1168.02   804.8 1180.59   834.2 1184.95   883.1 1186.29   932.1 1185.11
#Mann= 3 , 0 , 0
       0     0.1       0   468.8   0.045       0   483.8     0.1       0
Bank Sta=   468.8,   483.8
Exp/Cntr=0.3,0.1

Type RM Length L Ch R = 1 ,2110.5,383.647,383.805,385.412
XS GIS Cut Line= 3
     1764560.259      395366.187     1764141.246      395519.969
     1763688.169      395739.610
#Sta/Elev= 30
       0 1137.79    38.8 1124.99    87.3 1116.73   116.4 1107.91   135.8 1098.25
   145.5 1095.33   165.0 1083.92   184.4 1077.10   262.0 1060.41   329.9 1050.79
   349.3 1043.80   368.7 1032.52   378.4 1030.51   397.8 1022.29   426.9 1014.52
   438.8 1013.89   453.8 1013.89   504.4 1011.83   514.1 1012.45   533.5 1021.48
   601.3 1047.23   630.3 1065.94   649.7 1074.86   659.4 1081.42   669.0 1084.41
   698.1 1101.43   833.7 1134.01   901.4 1151.89   930.5 1162.26   949.8 1165.61
#Mann= 3 , 0 , 0
       0     0.1       0   438.8   0.045       0   453.8     0.1       0
Bank Sta=   438.8,   453.8
Exp/Cntr=0.3,0.1

Type RM Length L Ch R = 1 ,1726.7,386.189,390.756,394.797
XS GIS Cut Line= 3
     1764394.864      395059.008     1763960.952      395227.946
     1763519.942      395330.775
#Sta/Elev= 30
       0 1111.16    77.6 1087.51   164.9 1053.04   184.3 1048.48   203.7 1047.26
   252.2 1032.12   300.7 1021.47   320.1 1015.14   349.2 1010.68   439.2 1004.44
   446.2 1003.06   454.2 1005.22   465.6 1009.95   475.3 1020.54   484.9 1026.94
   494.5 1030.47   513.8 1042.43   533.1 1051.62   542.7 1058.33   610.2 1096.31
   619.8 1098.56   639.1 1108.31   668.0 1119.58   677.6 1121.17   706.5 1131.75
   764.3 1155.10   793.2 1164.75   812.5 1168.14   870.3 1169.52   918.5 1164.25
#Mann= 3 , 0 , 0
       0     0.1       0   439.2   0.045       0   454.2     0.1       0
Bank Sta=   439.2,   454.2
Exp/Cntr=0.3,0.1

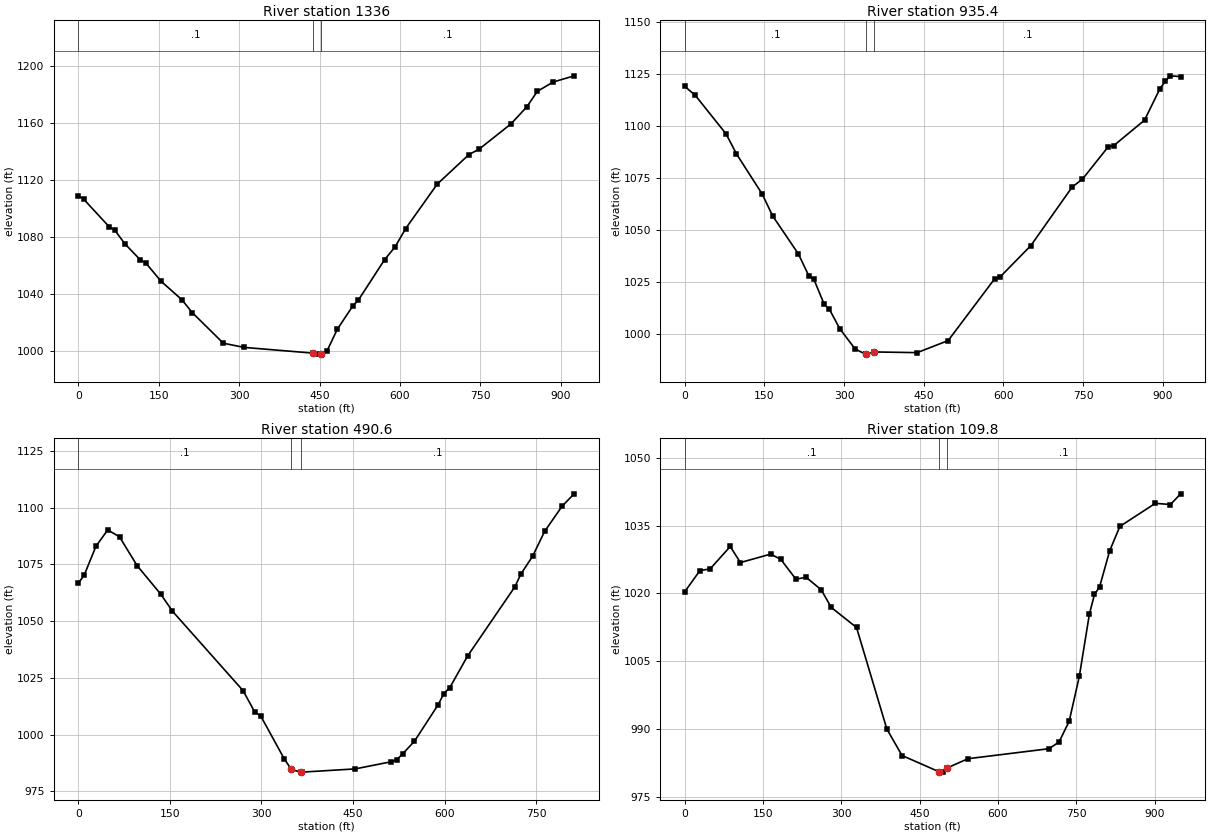
Type RM Length L Ch R = 1 ,1336,388.123,400.54,412.789
XS GIS Cut Line= 3
     1764300.278      394775.181     1763833.823      394855.539
     1763386.865      394921.277
#Sta/Elev= 30
       0 1108.90     9.7 1106.49    58.0 1086.83    67.6 1084.80    86.9 1075.00
   115.9 1063.64   125.6 1061.63   154.6 1048.63   193.2 1035.73   212.5 1026.71
   270.5 1005.18   309.1 1002.24   438.2  998.20   444.3  997.51   453.2  997.62
   463.7  999.52   483.1 1014.91   512.6 1031.65   522.4 1035.40   571.5 1063.93
   591.2 1072.97   610.8 1085.78   669.7 1117.00   728.7 1137.70   748.3 1141.70
   807.2 1159.27   836.7 1171.22   856.3 1182.14   885.8 1188.69   925.1 1193.06
#Mann= 3 , 0 , 0
       0     0.1       0   438.2   0.045       0   453.2     0.1       0
Bank Sta=   438.2,   453.2
Exp/Cntr=0.3,0.1

Type RM Length L Ch R = 1 ,935.4,460.312,444.837,429.386
XS GIS Cut Line= 3
     1764307.535      394618.619     1763865.368      394468.912
     1763413.419      394351.614
#Sta/Elev= 30
       0 1119.10    19.5 1114.89    77.8 1096.21    97.3 1086.60   145.9 1067.19
   165.3 1056.79   214.0 1038.36   233.4 1027.97   243.1 1026.18   262.6 1014.11
   272.3 1011.75   291.8 1002.41   320.9  992.58   340.4  990.15   341.1  990.20
   356.1  991.20   437.6  990.87   496.0  996.69   583.6 1026.48   593.3 1027.21
   651.6 1042.42   729.5 1070.66   748.9 1074.47   797.6 1090.11   807.3 1090.50
   865.7 1102.86   894.8 1118.05   904.6 1121.55   914.3 1124.22   933.7 1123.83
#Mann= 3 , 0 , 0
       0     0.1       0   341.1   0.045       0   356.1     0.1       0
Bank Sta=   341.1,   356.1
Exp/Cntr=0.3,0.1

Type RM Length L Ch R = 1 ,490.6,389.047,380.743,372.415
XS GIS Cut Line= 3
     1764173.790      393977.530     1763836.188      394092.376
     1763404.552      394238.700
#Sta/Elev= 30
       0 1066.71     9.6 1070.22    28.9 1082.96    48.2 1090.15    67.5 1087.08
    96.4 1074.38   134.9 1061.90   154.2 1054.36   269.9 1019.38   289.1 1009.95
   298.8 1008.25   337.3  989.38   349.1  984.67   364.1  983.51   366.3  983.50
   453.6  984.92   511.8  988.03   521.5  988.86   531.2  991.51   550.5  997.02
   589.3 1013.05   599.0 1018.11   608.7 1020.73   637.8 1034.63   715.4 1065.15
   725.1 1070.71   744.5 1078.63   763.9 1089.45   793.0 1100.72   812.4 1106.03
#Mann= 3 , 0 , 0
       0     0.1       0   349.1   0.045       0   364.1     0.1       0
Bank Sta=   349.1,   364.1
Exp/Cntr=0.3,0.1

Type RM Length L Ch R = 1 ,109.8,110.801,109.849,108.897
XS GIS Cut Line= 3
     1764054.459      393504.034     1763706.689      393714.413
     1763289.472      394062.666
#Sta/Elev= 30
       0 1020.38    29.0 1025.06    48.4 1025.41    87.1 1030.37   106.5 1026.82
   164.5 1028.69   183.9 1027.53   212.9 1023.14   232.3 1023.58   261.3 1020.81
   280.6 1016.91   329.0 1012.48   387.1  990.05   416.2  984.21   487.1  980.62
   493.8  980.54   502.1  981.43   542.3  983.50   697.6  985.71   717.0  987.19
   736.4  991.78   755.8 1001.68   775.2 1015.49   784.9 1019.80   794.6 1021.43
   814.0 1029.43   833.5 1034.80   901.4 1039.90   930.5 1039.64   949.9 1042.00
#Mann= 3 , 0 , 0
       0     0.1       0   487.1   0.045       0   502.1     0.1       0
Bank Sta=   487.1,   502.1
Exp/Cntr=0.3,0.1